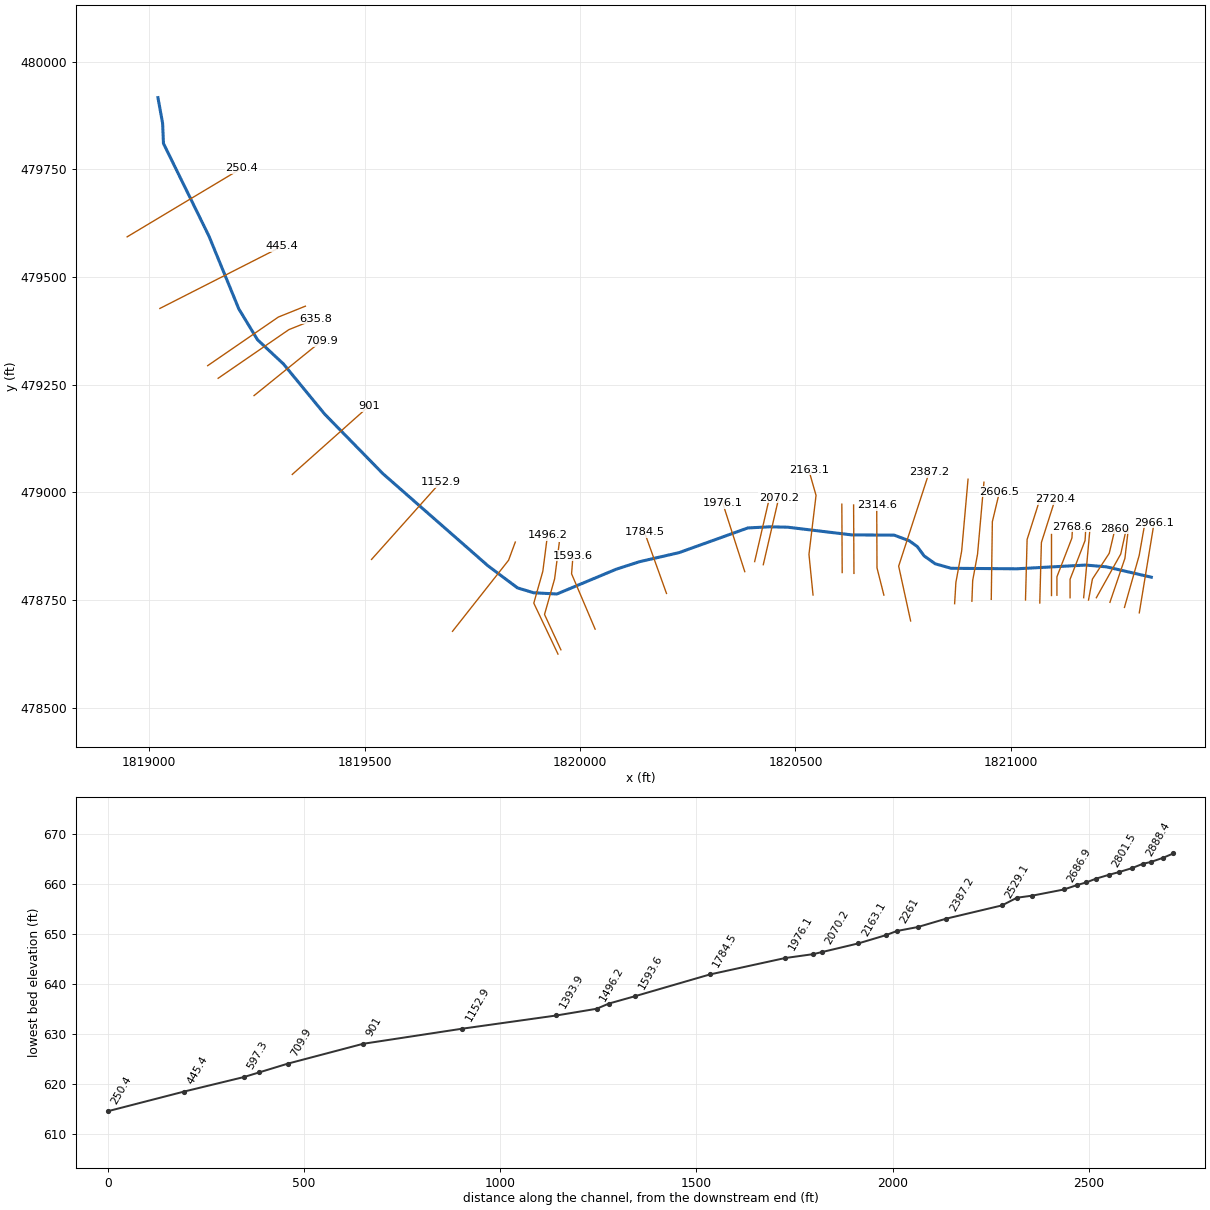
--- COALFK.prj (project) ---

Proj Title=COALFK
Current Plan=p01
Default Exp/Contr=0,0
English Units
Geom File=g01
Flow File=f01
Plan File=p01
BEGIN DESCRIPTION:
END DESCRIPTION:
DSS Export Rating Curves= 0
DSS Export Rating Curve Sorted= 0
DSS Export Volume Flow Curves= 0
DXF OffsetX= 0
DXF OffsetY= 0
DXF ScaleX= 0
DXF ScaleY= 0

--- COALFK.p01 (plan) ---

Plan Title=Floodplain
Program Version=4.00
Geom File=g01
Flow File=f01
K Sum by GR=0
Std Step Tol=0.01
Critical Tol=0.01
Num of Std Step Trials=20
Max Error Tol=0.3
Flow Tol Ratio=0.001
Split Flow NTrial=30
Split Flow Tol=0.02
Split Flow Ratio=0.02
Log Output Level=0
Friction Slope Method=1
Unsteady Friction Slope Method=2
Unsteady Bridges Friction Slope Method=1
Global Log Level=0
CheckData=False
Run HTab=0
Run UNet=0
Run PostProcess=0
UNET Theta=0
UNET Theta Warmup=0
UNET ZTol=0
UNET ZSATol=0
UNET MxIter=0
UNET MaxInSteps=0
UNET DtIC=0
UNET DtMin=0
UNET MaxCRTS=0
UNET WFStab=0
UNET SFStab=0
UNET WFX=0
UNET SFX=0
UNET DSS MLevel=0
UNET DZMax Abort=0
UNET Convert EG Bridges=0
UNET Use Existing IB Tables=0
UNET Froude Limit=0
UNET Froude Power=0
Write IC File=0
Echo Input=False
Echo Output=False
Write Detailed=0

--- COALFK.f01 (steady flow) ---

Flow Title=NFF Regression Equation
Program Version=4.10
Number of Profiles= 1
Profile Names=P100yr
River Rch & RM=COALFK,Main            ,2966.1
886.1313
River Rch & RM=COALFK,Main            ,1496.2
904.3825
River Rch & RM=COALFK,Main            ,1152.9
1073.524
River Rch & RM=COALFK,Main            ,597.3
1081.772
Boundary for River Rch & Prof#=COALFK,Main            , 1
Up Type= 0
Dn Type= 3
Dn Slope=0.02
DSS Import GetInterval= 0
DSS Import GetPeak= 0
DSS Import FillOption= 0

--- COALFK.g01 (geometry) ---

Geom Title=USGS 10m DEM
Program Version=4.10

River Reach=COALFK          ,Main
Reach XY= 30
     1821326.052      478803.132     1821222.005      478827.178
     1821173.672      478831.344     1821013.672      478822.663
     1820861.588      478823.844     1820824.505      478834.261
     1820798.672      478852.594     1820782.838      478874.261
     1820764.361      478887.627     1820729.264      478900.788
     1820630.755      478901.344     1820481.588      478919.261
     1820439.922      478920.094     1820389.567      478917.501
     1820229.895      478860.191     1820137.908      478839.087
     1820084.088      478821.726     1819946.304      478764.165
     1819892.248      478767.039     1819854.922      478778.323
      1819785.92      478829.985     1819542.505      479043.442
     1819407.268      479181.755     1819311.519      479298.289
     1819251.399      479354.347     1819207.997      479425.962
     1819138.552      479595.233      1819033.12      479809.983
     1819031.131      479856.735     1819020.301      479916.273

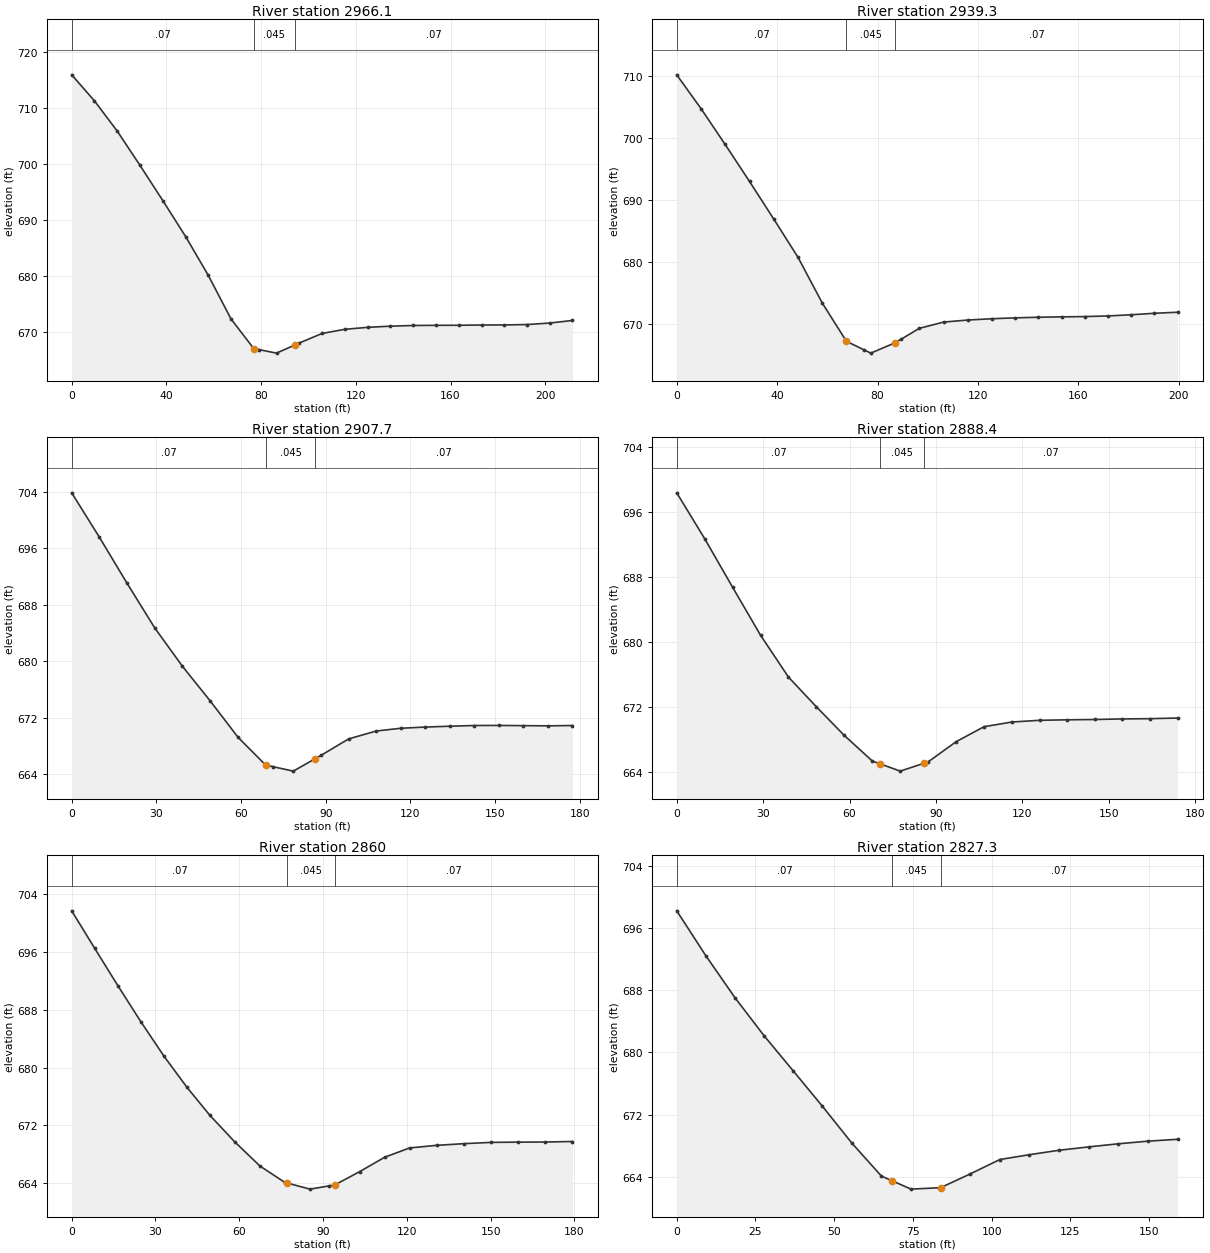
Type RM Length L Ch R = 1 ,2966.1  ,29.3,26.8,24.2
XS GIS Cut Line= 2
     1821298.117      478720.418     1821332.444      478929.143
#Sta/Elev= 25
       0     716     9.6  711.34    19.2  705.94    28.8  699.81    38.5  693.46
    48.1  687.04    57.7  680.07    67.3  672.26    76.9  666.96    79.3  666.76
    86.5  666.15    94.3  667.62    96.2  667.98   105.8  669.68   115.4  670.42
     125  670.77   134.6  670.98   144.2   671.1   153.8  671.13   163.4  671.14
   173.1  671.19   182.7   671.2   192.3  671.27   201.9  671.54   211.5     672
#Mann= 3 , 0 , 0
       0     .07       0    76.9    .045       0    94.3     .07       0
Bank Sta=76.9,94.3
XS Rating Curve= 0 ,0
Exp/Cntr=0.3,0.1

Type RM Length L Ch R = 1 ,2939.3  ,32.7,31.5,30.4
XS GIS Cut Line= 3
     1821263.705      478733.049     1821297.937      478853.928
     1821310.773      478926.669
#Sta/Elev= 24
       0  710.24     9.7  704.76    19.3  698.98      29     693    38.7   686.9
    48.3  680.75      58  673.34    67.6  667.17    74.4  665.83    77.3  665.26
      87  666.93    89.4  667.51    96.6  669.26   106.3  670.28     116  670.61
   125.6  670.82   134.9  670.96   144.1  671.06   153.3  671.12   162.6  671.17
   171.8  671.27     181  671.46   190.3   671.7   199.5  671.87
#Mann= 3 , 0 , 0
       0     .07       0    67.6    .045       0      87     .07       0
Bank Sta=67.6,87
XS Rating Curve= 0 ,0
Exp/Cntr=0.3,0.1

Type RM Length L Ch R = 1 ,2907.7  ,23.6,19.3,15.1
XS GIS Cut Line= 3
     1821230.009      478744.816     1821264.775      478846.974
     1821272.798      478915.971
#Sta/Elev= 22
       0  703.88     9.8  697.59    19.6  691.06    29.4  684.73    39.2  679.29
      49   674.4    58.9  669.22    68.7  665.27    71.3  665.04    78.5  664.41
    86.3  666.18    88.3  666.64    98.1  668.98   107.9   670.1   116.6  670.49
   125.3  670.66     134  670.78   142.6  670.88   151.3  670.89     160  670.86
   168.7  670.83   177.4  670.88
#Mann= 3 , 0 , 0
       0     .07       0    68.7    .045       0    86.3     .07       0
Bank Sta=68.7,86.3
XS Rating Curve= 0 ,0
Exp/Cntr=0.3,0.1

Type RM Length L Ch R = 1 ,2888.4  ,30.8,28.4,26
XS GIS Cut Line= 3
     1821198.452      478755.513     1821255.148      478857.137
     1821267.449      478913.297
#Sta/Elev= 21
       0  698.36     9.7  692.71    19.4  686.73    29.1  680.82    38.8  675.66
    48.5     672    58.2  668.47    67.9  665.33    70.7  664.97    77.6  664.08
    85.7  665.03    87.3  665.22      97   667.7   106.7  669.55   116.4  670.13
     126  670.34   135.5   670.4   145.1  670.44   154.7  670.51   164.3  670.54
   173.9  670.62
#Mann= 3 , 0 , 0
       0     .07       0    70.7    .045       0    85.7     .07       0
Bank Sta=70.7,85.7
XS Rating Curve= 0 ,0
Exp/Cntr=0.3,0.1

Type RM Length L Ch R = 1 ,2860    ,20.8,32.7,44.7
XS GIS Cut Line= 4
     1821180.267      478750.164      1821189.36      478798.837
     1821228.405      478858.741     1821241.776      478915.437
#Sta/Elev= 23
       0   701.7     8.2  696.53    16.5  691.36    24.8  686.33      33  681.61
    41.3  677.26    49.5  673.39    58.4  669.72    67.4  666.39    76.3  664.12
    77.2  664.03    85.3  663.19    92.2  663.64    94.2  663.77   103.1  665.61
   112.1  667.61     121  668.89   130.7  669.25   140.4  669.48   150.2  669.66
   159.8  669.69   169.6  669.71   179.3  669.78
#Mann= 3 , 0 , 0
       0     .07       0    77.2    .045       0    94.2     .07       0
Bank Sta=77.2,94.2
XS Rating Curve= 0 ,0
Exp/Cntr=0.3,0.1

Type RM Length L Ch R = 1 ,2827.3  ,32.4,25.7,19.1
XS GIS Cut Line= 3
     1821169.035      478755.513     1821173.314      478801.511
     1821183.476      478913.832
#Sta/Elev= 20
       0   698.2     9.2  692.45    18.5  687.02    27.7  682.15      37  677.61
    46.2  673.09    55.6  668.33      65  664.08    68.4  663.48    74.4  662.41
    83.4  662.59    83.8   662.6    93.2  664.37   102.6  666.22     112  666.84
   121.4  667.41   130.8  667.84   140.2  668.24   149.6  668.58     159  668.82
#Mann= 3 , 0 , 0
       0     .07       0    68.4    .045       0    83.8     .07       0
Bank Sta=68.4,83.8
XS Rating Curve= 0 ,0
Exp/Cntr=0.3,0.1

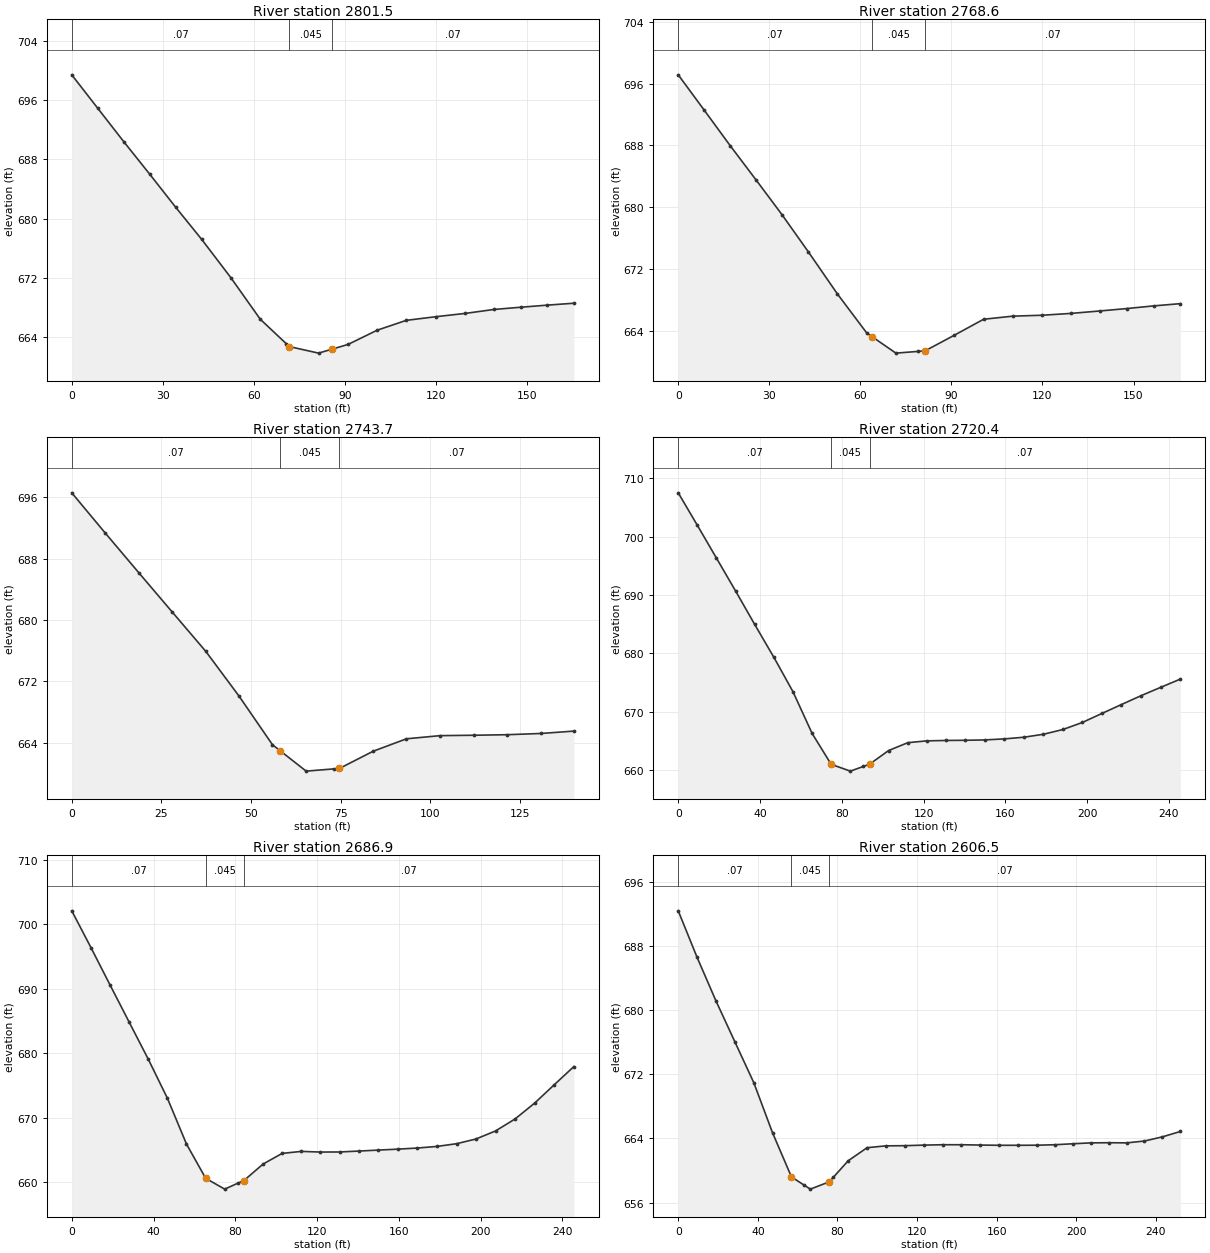
Type RM Length L Ch R = 1 ,2801.5  ,33.3,33,32.8
XS GIS Cut Line= 4
     1821137.478      478755.513     1821137.478      478798.302
     1821172.244      478888.159     1821173.849      478914.367
#Sta/Elev= 21
       0  699.39     8.6  694.86    17.1  690.39    25.7  685.98    34.2  681.55
    42.8   677.2    52.4  672.04    62.1  666.43    70.7  663.12    71.7  662.74
    81.3  661.86    85.7  662.39      91  663.03   100.6  664.95   110.2  666.28
   119.9  666.77   129.5  667.21   139.1  667.75   147.9  668.05   156.6  668.33
   165.4  668.59
#Mann= 3 , 0 , 0
       0     .07       0    71.7    .045       0    85.7     .07       0
Bank Sta=71.7,85.7
XS Rating Curve= 0 ,0
Exp/Cntr=0.3,0.1

Type RM Length L Ch R = 1 ,2768.6  ,15.8,24.9,33.7
XS GIS Cut Line= 4
     1821106.991      478761.397     1821106.991      478804.185
     1821141.757      478894.042     1821143.362       478920.25
#Sta/Elev= 21
       0  697.15     8.6  692.55    17.1  687.98    25.7   683.5    34.2  679.02
    42.8  674.25    52.4  668.78    62.1   663.7    63.9  663.21    71.7  661.09
    78.9  661.31    81.3  661.38      91  663.42   100.6  665.48   110.2  665.88
   119.9     666   129.5  666.24   139.1  666.56   147.9  666.87   156.6  667.21
   165.4   667.5
#Mann= 3 , 0 , 0
       0     .07       0    63.9    .045       0    81.3     .07       0
Bank Sta=63.9,81.3
XS Rating Curve= 0 ,0
Exp/Cntr=0.3,0.1

Type RM Length L Ch R = 1 ,2743.7  ,23.8,23.3,22.6
XS GIS Cut Line= 2
      1821092.55      478763.001      1821092.55      478903.135
#Sta/Elev= 18
       0  696.56     9.3  691.35    18.7  686.16      28  681.06    37.4  675.92
    46.7  670.08      56  663.77    58.1     663    65.4  660.33    73.1  660.62
    74.7  660.68    84.1  662.92    93.4  664.54   102.8  664.95   112.1     665
   121.4  665.07   130.8  665.23   140.1  665.54
#Mann= 3 , 0 , 0
       0     .07       0    58.1    .045       0    74.7     .07       0
Bank Sta=58.1,74.7
XS Rating Curve= 0 ,0
Exp/Cntr=0.3,0.1

Type RM Length L Ch R = 1 ,2720.4  ,33.5,33.5,33.5
XS GIS Cut Line= 3
     1821067.172      478743.364     1821070.896      478883.646
     1821102.761       478983.92
#Sta/Elev= 29
       0  707.54     9.4  701.94    18.7  696.34    28.1  690.68    37.4  684.97
    46.8  679.32    56.1  673.45    65.5  666.27    74.8  660.98    75.6  660.88
    84.2  659.81    90.6  660.62    93.6     661   102.9  663.34   112.3  664.69
   121.6     665     131  665.07   140.3   665.1   149.9  665.16   159.5  665.34
     169  665.62   178.6  666.13   188.2  666.95   197.7  668.16   207.3  669.71
   216.8  671.23   226.4  672.75     236  674.18   245.6  675.59
#Mann= 3 , 0 , 0
       0     .07       0    74.8    .045       0    93.6     .07       0
Bank Sta=74.8,93.6
XS Rating Curve= 0 ,0
Exp/Cntr=0.3,0.1

Type RM Length L Ch R = 1 ,2686.9  ,80.2,80.5,80.8
XS GIS Cut Line= 3
     1821034.011      478750.317     1821037.734      478890.599
     1821069.599      478990.873
#Sta/Elev= 29
       0  702.07     9.4  696.36    18.7  690.59    28.1   684.8    37.4  679.08
    46.8     673    56.1  665.92    65.5   660.6    66.2  660.47    74.8  658.92
    81.2  659.83    84.2  660.25    93.6  662.81   102.9  664.46   112.3  664.77
   121.6  664.67     131  664.68   140.3  664.82   149.9  664.97   159.5  665.12
     169  665.29   178.6  665.54   188.2  665.96   197.7  666.69   207.3  667.94
   216.8  669.79   226.4  672.25     236   675.1   245.6  677.92
#Mann= 3 , 0 , 0
       0     .07       0    65.5    .045       0    84.2     .07       0
Bank Sta=65.5,84.2
XS Rating Curve= 0 ,0
Exp/Cntr=0.3,0.1

Type RM Length L Ch R = 1 ,2606.5  ,43.2,39.3,35.5
XS GIS Cut Line= 3
     1820954.556      478751.769      1820957.08      478932.012
     1820973.811      479002.084
#Sta/Elev= 30
       0  692.35     9.5  686.54      19  681.11    28.5  676.02      38  670.93
    47.4   664.7    56.9  659.21      63  658.23    66.4  657.69    75.9   658.6
      78  659.18    85.4  661.22    94.9  662.85   104.4  663.08   113.8   663.1
   123.3  663.17   132.8  663.22   142.3  663.22   151.8  663.18   161.3  663.15
   170.8  663.15   180.3  663.16   189.3  663.22   198.3  663.34   207.3  663.45
   216.3  663.47   225.3  663.45   234.3  663.68   243.3   664.2   252.3  664.87
#Mann= 3 , 0 , 0
       0     .07       0    56.9    .045       0    75.9     .07       0
Bank Sta=56.9,75.9
XS Rating Curve= 0 ,0
Exp/Cntr=0.3,0.1

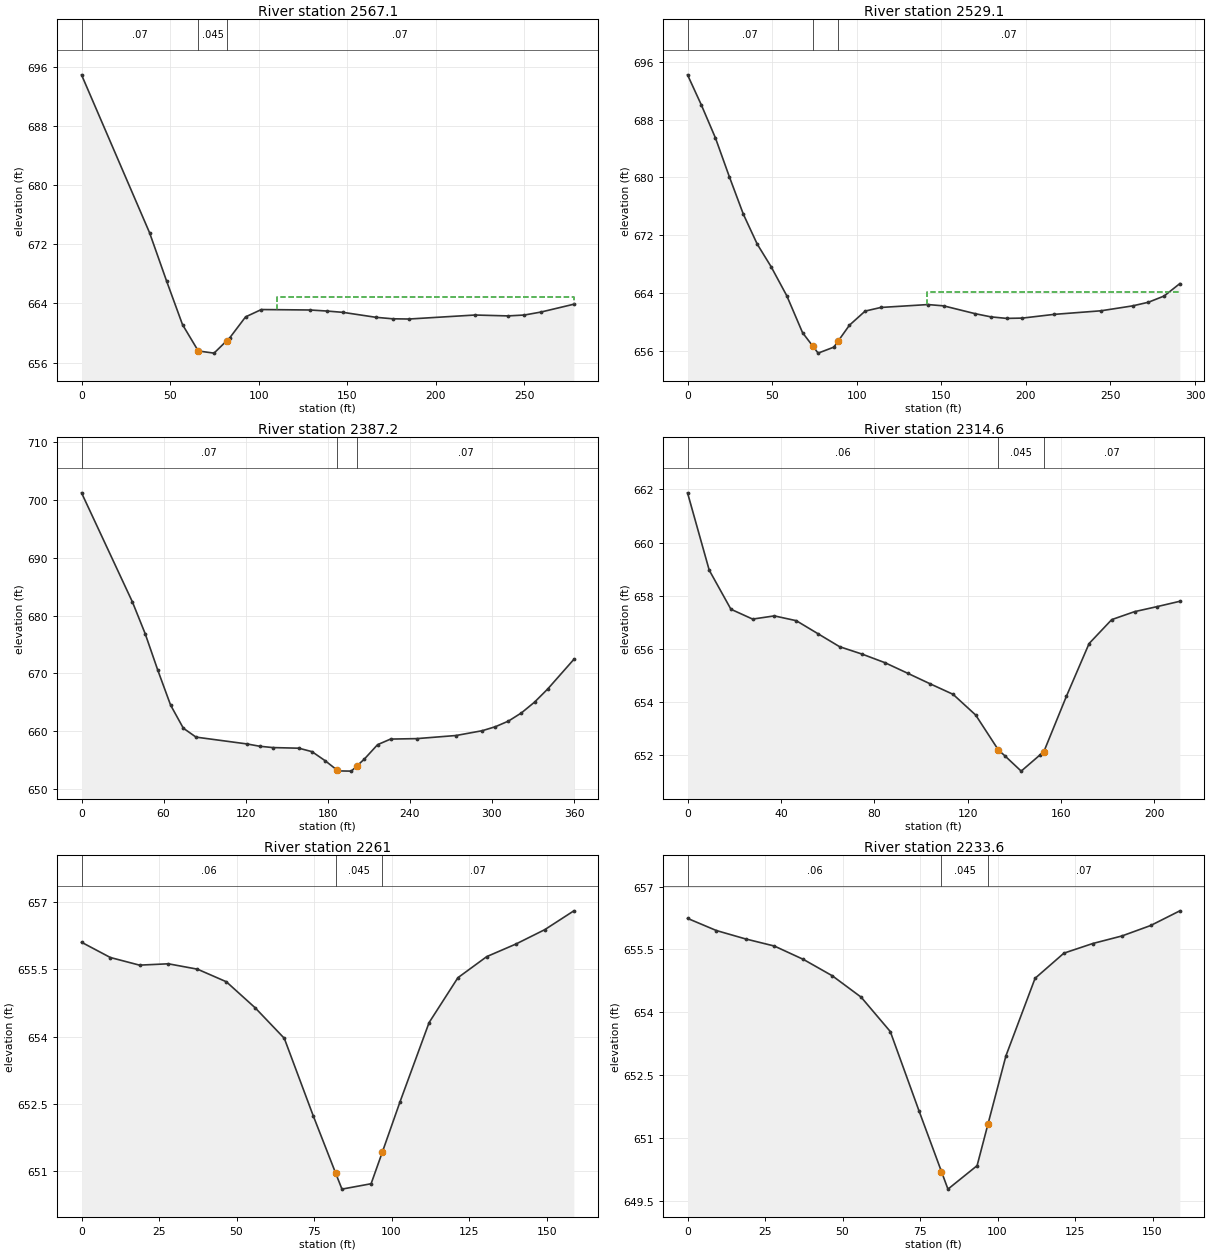
Type RM Length L Ch R = 1 ,2567.1  ,37.9,38,38
XS GIS Cut Line= 4
     1820909.627       478747.49      1820911.46      478795.488
     1820922.735      478856.867     1820937.559      479023.652
#Sta/Elev= 21
       0  694.88    38.4  673.54      48  667.02      57  661.12    65.9  657.56
    74.8  657.27    81.9  658.93    83.7  659.35    92.6  662.17   101.5  663.16
     129   663.1   138.4  662.96   147.6  662.78   166.2  662.11   175.6  661.91
   184.9  661.88   222.1  662.42   240.7   662.3     250  662.42   259.3  662.82
   277.9  663.88
#Mann= 3 , 0 , 0
       0     .07       0    65.9    .045       0    81.9     .07       0
#XS Ineff= 2 , 0
                          110.23          664.88
Permanent Ineff=
       F       F
Bank Sta=65.9,81.9
XS Rating Curve= 0 ,0
Exp/Cntr=0.3,0.1

Type RM Length L Ch R = 1 ,2529.1  ,144.9,141.9,138.9
XS GIS Cut Line= 4
     1820869.513      478741.607     1820872.446      478790.963
      1820885.83       478863.82     1820900.653      479030.605
#Sta/Elev= 28
       0  694.18     8.2     690    16.5  685.46    24.7  680.11      33  674.92
    41.2  670.79    49.4  667.67    58.7  663.64      68  658.55    74.1  656.68
    77.2  655.73    86.5  656.56    89.1  657.42    95.7  659.59     105  661.54
   114.3  662.04   142.1  662.44   151.4  662.26     170  661.18   179.3  660.74
   188.6  660.53   197.9  660.57   216.5  661.08   244.4  661.58   263.1  662.26
   272.4  662.76   281.7  663.62     291  665.34
#Mann= 3 , 0 , 0
       0     .07       0    74.1    .045       0    89.1     .07       0
#XS Ineff= 2 , 0
                          141.78          664.19
Permanent Ineff=
       F       F
Bank Sta=74.1,89.1
XS Rating Curve= 0 ,0
Exp/Cntr=0.3,0.1

Type RM Length L Ch R = 1 ,2387.2  ,65.3,72.5,79.8
XS GIS Cut Line= 3
     1820767.389      478701.598     1820739.611       478828.82
     1820810.627      479047.255
#Sta/Elev= 29
       0  701.28    37.2  682.38    46.5   676.9    55.8  670.53    65.1  664.52
    74.4  660.52    83.7  658.97   120.9  657.79   130.2  657.39   139.8  657.16
   158.9  657.05   168.5  656.45   178.1  654.88   186.5  653.32   187.6  653.12
   197.2  653.08   201.5  654.02   206.8  655.18   216.4  657.66   225.9  658.63
   245.1  658.71   273.8  659.25   292.9  660.08   302.5  660.77   312.1  661.75
   321.6  663.17   331.2  665.04   340.8  667.31   359.9  672.44
#Mann= 3 , 0 , 0
       0     .07       0   186.5    .045       0   201.5     .07       0
Bank Sta=186.5,201.5
XS Rating Curve= 0 ,0
Exp/Cntr=0.3,0.1

Type RM Length L Ch R = 1 ,2314.6  ,53.6,53.6,53.6
XS GIS Cut Line= 3
     1820705.312      478761.528     1820689.339      478824.722
     1820688.645      478970.556
#Sta/Elev= 25
       0  661.87     9.3  658.96    18.6  657.49    27.9  657.12    37.2  657.24
    46.6  657.06    55.9  656.57    65.2  656.08    74.9   655.8    84.6  655.48
    94.4  655.08   104.1  654.68   113.8  654.29   123.5  653.51   133.2   652.2
   136.2  651.96     143   651.4   151.2  652.02   152.7  652.13   162.4  654.22
   172.1   656.2   181.8   657.1   191.6   657.4   201.3  657.59     211  657.79
#Mann= 3 , 0 , 0
       0     .06       0   133.2    .045       0   152.7     .07       0
Bank Sta=133.2,152.7
XS Rating Curve= 0 ,0
Exp/Cntr=0.3,0.1

Type RM Length L Ch R = 1 ,2261    ,27.5,27.4,27.5
XS GIS Cut Line= 2
     1820635.841       478812.04     1820635.008       478970.79
#Sta/Elev= 20
       0   656.1     9.3  655.76    18.7  655.59      28  655.62    37.4   655.5
    46.7  655.22      56  654.64    65.4  653.96    74.7  652.24      82  650.95
      84   650.6    93.4  650.72      97  651.42   102.7  652.54   112.1  654.31
   121.4  655.31   130.7  655.78   140.1  656.06   149.4  656.38   158.8   656.8
#Mann= 3 , 0 , 0
       0     .06       0      82    .045       0      97     .07       0
Bank Sta=82,97
XS Rating Curve= 0 ,0
Exp/Cntr=0.3,0.1

Type RM Length L Ch R = 1 ,2233.6  ,73.2,70.5,67.6
XS GIS Cut Line= 2
     1820608.549      478813.915     1820607.716      478972.665
#Sta/Elev= 20
       0  656.24     9.3  655.95    18.7  655.75      28  655.58    37.4  655.26
    46.7  654.87      56  654.36    65.4  653.54    74.7  651.64    81.9   650.2
      84  649.78    93.4  650.34    96.9  651.33   102.7  652.96   112.1  654.81
   121.4  655.41   130.7  655.64   140.1  655.82   149.4  656.07   158.8  656.42
#Mann= 3 , 0 , 0
       0     .06       0    81.9    .045       0    96.9     .07       0
Bank Sta=81.9,96.9
XS Rating Curve= 0 ,0
Exp/Cntr=0.3,0.1

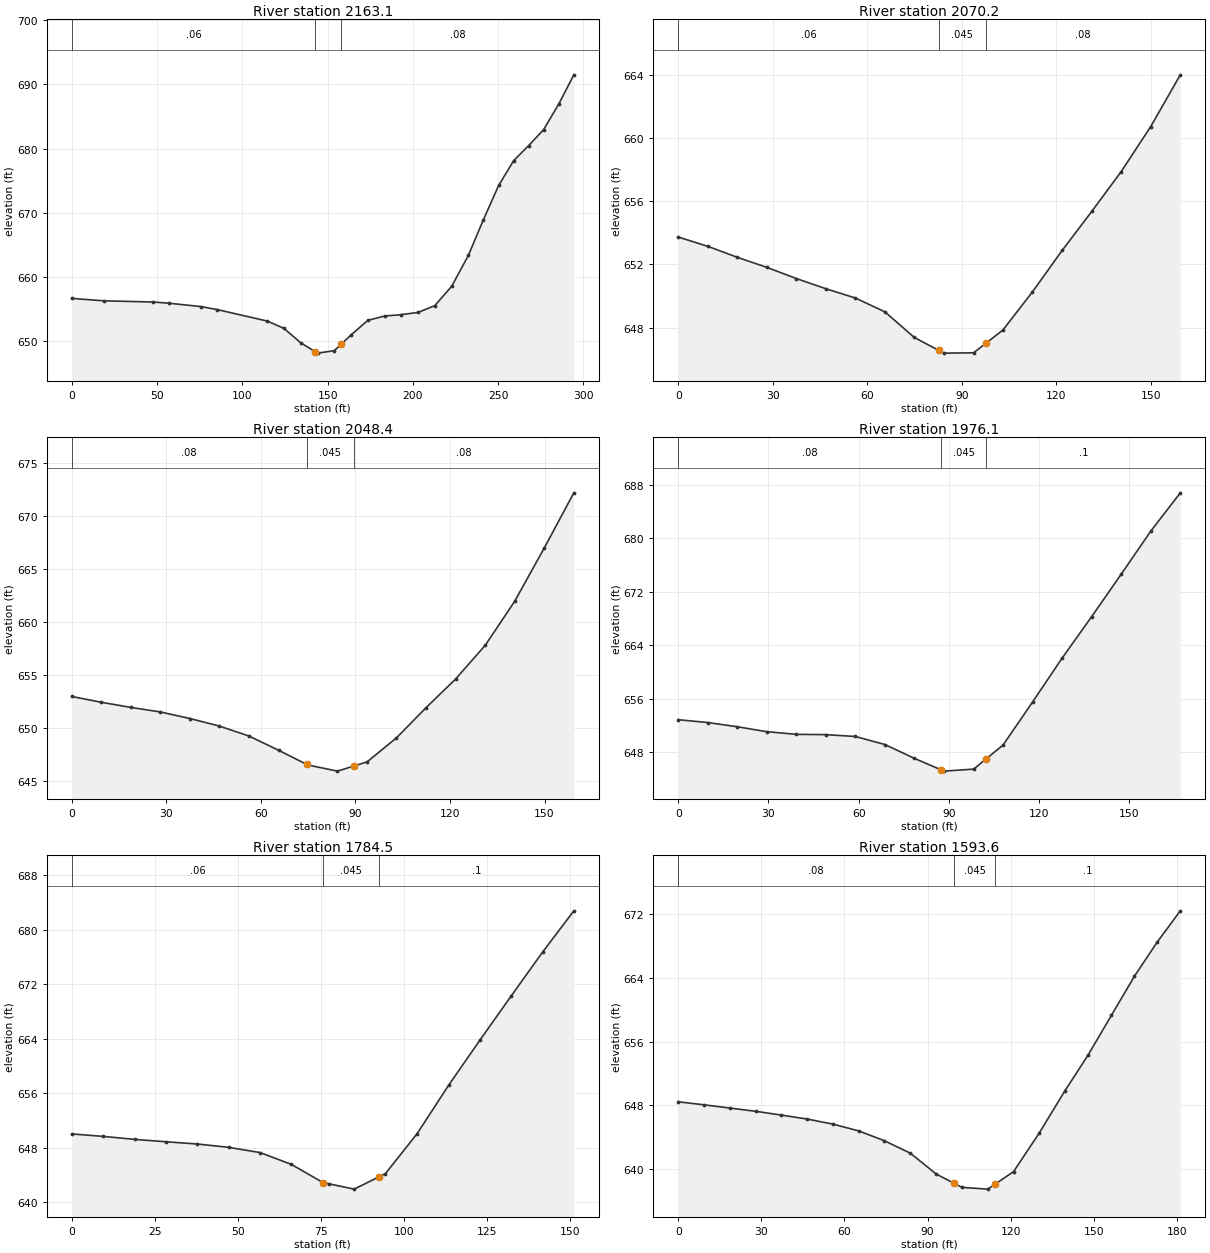
Type RM Length L Ch R = 1 ,2163.1  ,95.7,92.9,90.6
XS GIS Cut Line= 4
     1820540.861      478761.876     1820531.416       478856.32
     1820547.833      478993.033     1820530.861      479052.431
#Sta/Elev= 28
       0  656.65      19  656.27    47.5  656.09      57   655.9    75.9  655.37
    85.4   654.9   114.6  653.12   124.4  651.98   134.3  649.72   142.9  648.32
   144.1  648.12   153.9   648.5   157.9  649.49   163.8  650.96   173.6  653.23
   183.4   653.9   193.3  654.12   203.1  654.47   212.9  655.53   222.8  658.55
   232.6  663.38   241.4  668.94   250.3  674.25   259.1  678.12   267.9  680.47
   276.7  682.97   285.6  686.97   294.4   691.5
#Mann= 3 , 0 , 0
       0     .06       0   142.9    .045       0   157.9     .08       0
Bank Sta=142.9,157.9
XS Rating Curve= 0 ,0
Exp/Cntr=0.3,0.1

Type RM Length L Ch R = 1 ,2070.2  ,21.8,21.9,21.8
XS GIS Cut Line= 2
     1820425.362      478832.157     1820461.307      478987.305
#Sta/Elev= 20
       0  653.73     9.4  653.14    18.7  652.45    28.1  651.81    37.5   651.1
    46.8  650.46    56.2  649.87    65.6  648.99    74.9  647.37    82.6  646.56
    84.3  646.38    93.7   646.4    97.6     647     103  647.84   112.4  650.26
   121.8  652.88   131.2  655.35   140.5  657.86   149.9  660.72   159.3     664
#Mann= 3 , 0 , 0
       0     .06       0    82.6    .045       0    97.6     .08       0
Bank Sta=82.6,97.6
XS Rating Curve= 0 ,0
Exp/Cntr=0.3,0.1

Type RM Length L Ch R = 1 ,2048.4  ,59.7,72.3,84.3
XS GIS Cut Line= 2
     1820405.362       478839.38     1820441.307      478994.527
#Sta/Elev= 20
       0  653.01     9.4  652.46    18.7  651.98    28.1  651.55    37.5  650.93
    46.8  650.22    56.2  649.28    65.6  647.94    74.5  646.61    74.9  646.55
    84.3  645.97    89.5  646.45    93.7  646.84     103   649.1   112.4  651.95
   121.8  654.66   131.2  657.84   140.5  661.97   149.9     667   159.3  672.21
#Mann= 3 , 0 , 0
       0     .08       0    74.5    .045       0    89.5     .08       0
Bank Sta=74.5,89.5
XS Rating Curve= 0 ,0
Exp/Cntr=0.3,0.1

Type RM Length L Ch R = 1 ,1976.1  ,190.8,191.6,192.3
XS GIS Cut Line= 2
     1820382.389      478816.042     1820331.278      478974.931
#Sta/Elev= 20
       0  652.87     9.8  652.45    19.6  651.82    29.4  651.08    39.3  650.68
    49.1  650.64    58.9  650.36    68.7  649.16    78.5  647.09    87.4  645.37
    88.4  645.18    98.2  645.48   102.4  647.03     108  649.09   117.8  655.53
   127.6  662.08   137.4  668.27   147.3  674.67   157.1  681.09   166.9  686.81
#Mann= 3 , 0 , 0
       0     .08       0    87.4    .045       0   102.4      .1       0
Bank Sta=87.4,102.4
XS Rating Curve= 0 ,0
Exp/Cntr=0.3,0.1

Type RM Length L Ch R = 1 ,1784.5  ,189.5,190.9,192
XS GIS Cut Line= 2
     1820200.722      478765.487     1820149.611      478907.709
#Sta/Elev= 19
       0     650     9.4  649.64    18.9   649.2    28.3  648.85    37.8  648.52
    47.2  648.03    56.7  647.26    66.1  645.52    75.6  642.85    77.5  642.66
      85  641.89    92.5  643.71    94.4  644.17   103.9  650.02   113.4  657.14
   122.8  663.76   132.2  670.24   141.7  676.72   151.1  682.78
#Mann= 3 , 0 , 0
       0     .06       0    75.6    .045       0    92.5      .1       0
Bank Sta=75.6,92.5
XS Rating Curve= 0 ,0
Exp/Cntr=0.3,0.1

Type RM Length L Ch R = 1 ,1593.6  ,81.2,66,49.2
XS GIS Cut Line= 3
     1820035.077      478682.588     1819980.428      478811.049
     1819983.622      478852.568
#Sta/Elev= 23
       0  648.46     9.3  648.08    18.6  647.68    27.9  647.27    37.2   646.8
    46.5   646.3    55.8  645.67    65.2  644.81    74.4  643.59    83.8  642.02
    93.1  639.42    99.4  638.29   102.4  637.75   111.7  637.53   114.4  638.16
     121  639.71   130.3  644.56   139.6  649.86   147.9   654.3   156.3  659.26
   164.6  664.15   172.9  668.47   181.2  672.36
#Mann= 3 , 0 , 0
       0     .08       0    99.4    .045       0   114.4      .1       0
Bank Sta=99.4,114.4
XS Rating Curve= 0 ,0
Exp/Cntr=0.3,0.1

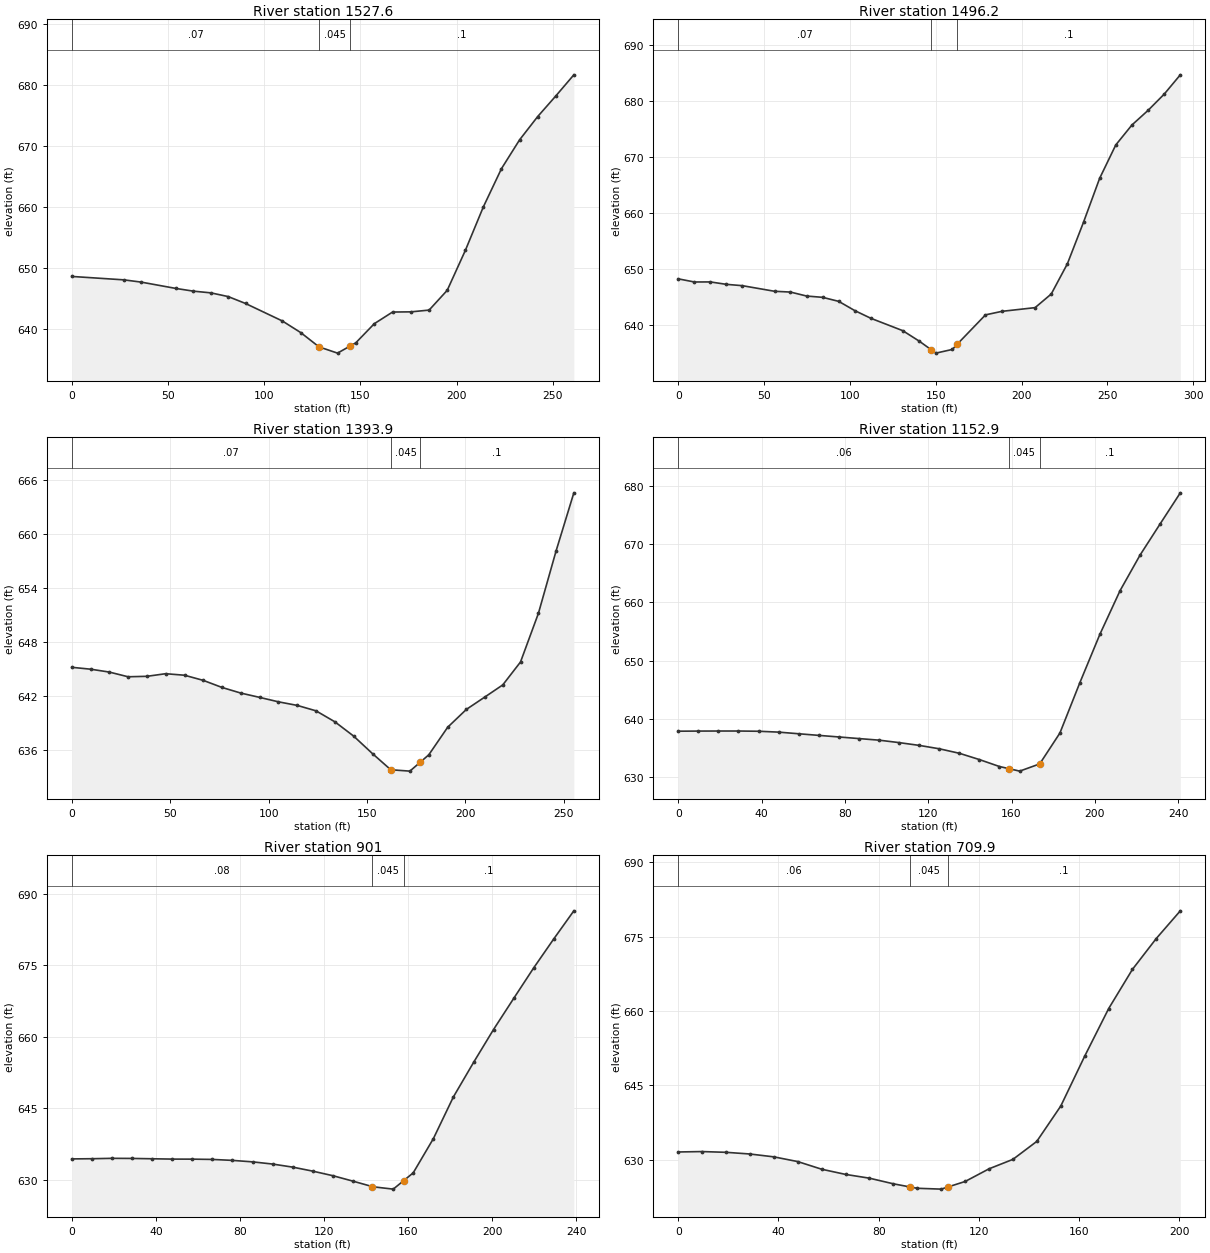
Type RM Length L Ch R = 1 ,1527.6  ,31.4,31.4,32.7
XS GIS Cut Line= 4
     1819955.588      478634.681     1819917.617      478716.655
     1819941.038      478799.339     1819951.833      478883.265
#Sta/Elev= 26
       0  648.63    27.1  648.07    36.1   647.7    54.2  646.66    63.2  646.22
    72.3  645.94    81.3  645.33    90.3   644.2   109.4  641.34     119  639.43
   128.5  637.09   138.1  636.07   144.8  637.26   147.6  637.76   157.2  640.89
   166.7   642.8   176.3  642.83   185.7  643.12   195.1  646.36   204.5  652.88
   213.9  660.04   223.3  666.29   232.7     671   242.1  674.81   251.5  678.18
   260.9  681.65
#Mann= 3 , 0 , 0
       0     .07       0   128.5    .045       0   144.8      .1       0
Bank Sta=128.5,144.8
XS Rating Curve= 0 ,0
Exp/Cntr=0.3,0.1

Type RM Length L Ch R = 1 ,1496.2  ,110.9,102.3,93.2
XS GIS Cut Line= 4
     1819948.845      478624.745      1819892.71      478742.934
     1819913.714      478817.082     1819924.509      478901.008
#Sta/Elev= 30
       0  648.28     9.4  647.72    18.7  647.73      28   647.3    37.4  647.06
    56.1  646.06    65.4  645.92    74.8  645.21    84.1  644.98    93.5  644.26
   102.8  642.62   112.2  641.24   130.8  639.03   140.5  637.14   147.4  635.62
   150.1  635.02   159.7  635.68   162.4  636.57     179  641.85   188.6  642.48
   207.9  643.14   217.3  645.57   226.7  650.96   236.1  658.38   245.5  666.22
   254.9  672.18   264.3  675.74   273.7  678.35   283.1  681.25   292.5   684.7
#Mann= 3 , 0 , 0
       0     .07       0   147.4    .045       0   162.4      .1       0
Bank Sta=147.4,162.4
XS Rating Curve= 0 ,0
Exp/Cntr=0.3,0.1

Type RM Length L Ch R = 1 ,1393.9  ,242.3,241,239.5
XS GIS Cut Line= 3
     1819704.041      478677.567     1819834.146      478842.463
      1819849.76      478884.692
#Sta/Elev= 29
       0   645.2     9.6  644.99    19.1  644.67    28.6  644.15    38.2   644.2
    47.7  644.49    57.3  644.32    66.8  643.75    76.4  642.96    85.9  642.34
    95.5  641.86     105  641.37   114.6  640.97   124.1  640.37   133.7  639.15
   143.2  637.57   152.8  635.62   162.1  633.83   171.8  633.68   177.1  634.68
   181.4  635.49     191  638.55   200.5  640.53     210  641.92     219  643.25
     228  645.79   237.1  651.19   246.1  658.13   255.1  664.56
#Mann= 3 , 0 , 0
       0     .07       0   162.1    .045       0   177.1      .1       0
Bank Sta=162.1,177.1
XS Rating Curve= 0 ,0
Exp/Cntr=0.3,0.1

Type RM Length L Ch R = 1 ,1152.9  ,254.5,251.9,249.3
XS GIS Cut Line= 2
     1819516.091      478844.388     1819676.682      479024.076
#Sta/Elev= 28
       0  637.88     9.6   637.9    19.3  637.91    28.9  637.91    38.6  637.87
    48.2  637.72    57.8  637.44    67.5  637.16    77.1  636.89    86.8  636.61
    96.4  636.34     106  635.92   115.7  635.44   125.3  634.86     135  634.08
   144.6     633   154.2  631.81   158.8  631.44   163.9  631.02   173.5  632.26
   173.8  632.42   183.2  637.56   192.8  646.23   202.4  654.53   212.1  662.04
   221.7  668.15   231.4  673.54     241  678.83
#Mann= 3 , 0 , 0
       0     .06       0   158.8    .045       0   173.5      .1       0
Bank Sta=158.8,173.5
XS Rating Curve= 0 ,0
Exp/Cntr=0.3,0.1

Type RM Length L Ch R = 1 ,901     ,192.1,191.1,190
XS GIS Cut Line= 2
     1819332.098      479041.715     1819510.432      479200.603
#Sta/Elev= 28
       0  634.35     9.6  634.39    19.1  634.47    28.7  634.45    38.2  634.38
    47.8  634.31    57.3   634.3    66.9  634.24    76.4  634.04      86  633.73
    95.5  633.27   105.1  632.62   114.6  631.78   124.2  630.82   133.8  629.67
   142.8  628.55   143.3  628.49   152.9     628   157.8  629.76   162.4  631.42
     172  638.62   181.5  647.37   191.1  654.62   200.6  661.54   210.2  668.08
   219.7  674.49   229.3  680.61   238.8  686.48
#Mann= 3 , 0 , 0
       0     .08       0   142.8    .045       0   157.8      .1       0
Bank Sta=142.8,157.8
XS Rating Curve= 0 ,0
Exp/Cntr=0.3,0.1

Type RM Length L Ch R = 1 ,709.9   ,76,74.1,72.3
XS GIS Cut Line= 2
     1819243.432      479224.687      1819399.21       479350.75
#Sta/Elev= 24
       0  631.54     9.5  631.62    19.1  631.47    28.6  631.13    38.2  630.55
    47.7   629.6    57.3  628.05    66.8  627.01    76.3  626.25    85.9  625.11
    92.5  624.48    95.4  624.21     105  624.04   107.5  624.45   114.5  625.58
   124.1  628.15   133.6  630.05   143.1  633.67   152.7  640.82   162.2  650.84
   171.8  660.48   181.3   668.4   190.8  674.62   200.4  680.21
#Mann= 3 , 0 , 0
       0     .06       0    92.5    .045       0   107.5      .1       0
Bank Sta=92.5,107.5
XS Rating Curve= 0 ,0
Exp/Cntr=0.3,0.1

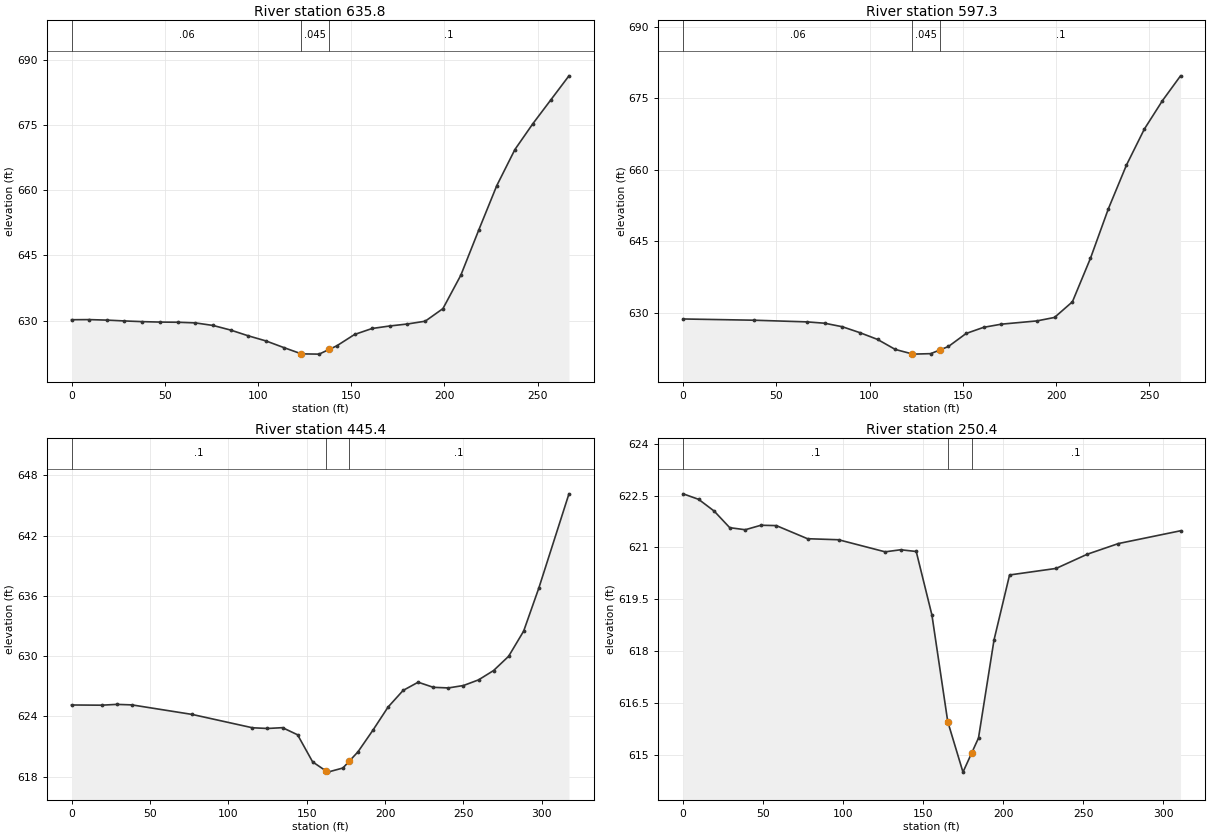
Type RM Length L Ch R = 1 ,635.8   ,38.4,38.4,38.5
XS GIS Cut Line= 3
     1819160.045       479264.86     1819324.134      479377.753
     1819386.846      479402.973
#Sta/Elev= 30
       0  630.19     9.5  630.22      19   630.1    28.4  629.91    37.9  629.75
    47.4  629.65    56.9  629.61    66.4  629.46    75.9  628.87    85.4   627.8
    94.8  626.48   104.3   625.3   113.8  623.78   123.3  622.32   132.8  622.26
   138.3  623.37   142.3  624.18   151.8  626.79   161.2  628.17   170.7  628.75
   180.2  629.21   189.7  629.85   199.2  632.75   208.8  640.45   218.5  650.96
   228.1  661.12   237.8  669.42   247.4  675.36   257.1  680.89   266.8  686.42
#Mann= 3 , 0 , 0
       0     .06       0   123.3    .045       0   138.3      .1       0
Bank Sta=123.3,138.3
XS Rating Curve= 0 ,0
Exp/Cntr=0.3,0.1

Type RM Length L Ch R = 1 ,597.3   ,155,152,149
XS GIS Cut Line= 3
     1819135.733      479294.125     1819299.822      479407.018
     1819362.533      479432.237
#Sta/Elev= 25
       0  628.71    37.9  628.45    66.4   628.1    75.9  627.82    85.4  627.08
    94.8  625.84   104.3  624.42   113.8  622.32   122.8  621.39   123.3  621.34
   132.8  621.44   137.8  622.23   142.3  622.94   151.8  625.67   161.2  626.96
   170.7  627.62   189.7   628.3   199.2  629.03   208.8  632.31   218.5  641.45
   228.1  651.82   237.8  660.98   247.4  668.53   257.1  674.48   266.8  679.68
#Mann= 3 , 0 , 0
       0     .06       0   122.8    .045       0   137.8      .1       0
Bank Sta=122.8,137.8
XS Rating Curve= 0 ,0
Exp/Cntr=0.3,0.1

Type RM Length L Ch R = 1 ,445.4   ,193.3,194.9,196.4
XS GIS Cut Line= 2
      1819024.85      479426.988     1819307.662      479570.832
#Sta/Elev= 28
       0  625.13    19.2  625.11    28.8  625.19    38.5  625.14    76.9  624.19
   115.4  622.86     125  622.79   134.6  622.87   144.2  622.16   153.8  619.46
   162.1  618.58   163.4  618.44   173.1  618.85   177.1  619.52   182.7  620.46
   192.3  622.63   201.9  624.92   211.5  626.58   221.1   627.4   230.8  626.89
   240.4  626.83     250  627.07   259.6  627.63   269.2  628.56   278.8  629.98
   288.4  632.49   298.1  636.79   317.3  646.17
#Mann= 3 , 0 , 0
       0      .1       0   162.1    .045       0   177.1      .1       0
Bank Sta=162.1,177.1
XS Rating Curve= 0 ,0
Exp/Cntr=0.3,0.1

Type RM Length L Ch R = 1 ,250.4   ,258.7,250.4,242.2
XS GIS Cut Line= 2
     1818948.808       479593.17     1819215.301      479752.892
#Sta/Elev= 23
       0  622.55     9.7  622.39    19.4  622.05    29.1  621.57    38.8  621.51
    48.6  621.64    58.2  621.63    77.7  621.25    97.1  621.22   126.2  620.87
   135.9  620.93   145.6  620.88   155.4  619.04   165.3  615.95   174.8  614.49
   180.3  615.05   184.5  615.48   194.2  618.32   203.9   620.2     233  620.39
   252.4   620.8   271.9  621.11   310.7  621.48
#Mann= 3 , 0 , 0
       0      .1       0   165.3    .045       0   180.3      .1       0
Bank Sta=165.3,180.3
XS Rating Curve= 0 ,0
Exp/Cntr=0.3,0.1

Chan Stop Cuts=-1
Use User Specified Reach Order=0
Composite Channel Slope=5